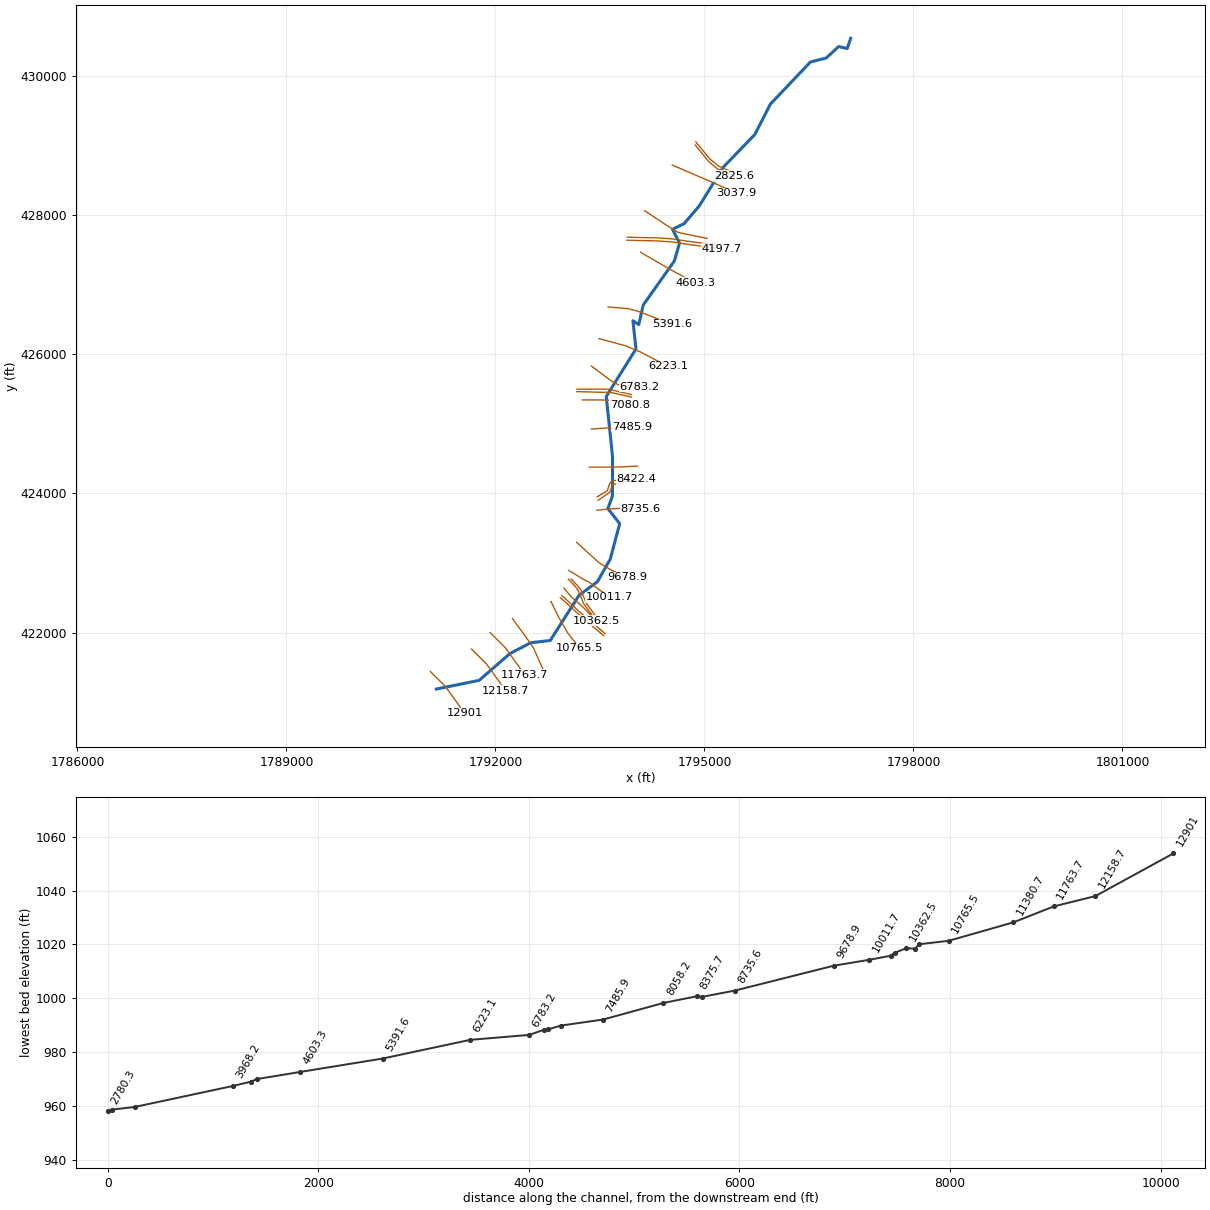
--- PedlarRun.prj (project) ---

Proj Title=PedlarRun
Current Plan=p01
Default Exp/Contr=0,0
English Units
Geom File=g01
Flow File=f01
Plan File=p01
BEGIN DESCRIPTION:
END DESCRIPTION:
DSS Export Rating Curves= 0
DSS Export Rating Curve Sorted= 0
DSS Export Volume Flow Curves= 0
DXF OffsetX= 0
DXF OffsetY= 0
DXF ScaleX= 0
DXF ScaleY= 0

--- PedlarRun.p01 (plan) ---

Plan Title=Floodplain
Program Version=4.00
Geom File=g01
Flow File=f01
K Sum by GR=0
Std Step Tol=0.01
Critical Tol=0.01
Num of Std Step Trials=20
Max Error Tol=0.3
Flow Tol Ratio=0.001
Split Flow NTrial=30
Split Flow Tol=0.02
Split Flow Ratio=0.02
Log Output Level=0
Friction Slope Method=1
Unsteady Friction Slope Method=2
Unsteady Bridges Friction Slope Method=1
Global Log Level=0
CheckData=False
Run HTab=0
Run UNet=0
Run PostProcess=0
UNET Theta=0
UNET Theta Warmup=0
UNET ZTol=0
UNET ZSATol=0
UNET MxIter=0
UNET MaxInSteps=0
UNET DtIC=0
UNET DtMin=0
UNET MaxCRTS=0
UNET WFStab=0
UNET SFStab=0
UNET WFX=0
UNET SFX=0
UNET DSS MLevel=0
UNET DZMax Abort=0
UNET Convert EG Bridges=0
UNET Use Existing IB Tables=0
UNET Froude Limit=0
UNET Froude Power=0
Write IC File=0
Echo Input=False
Echo Output=False
Write Detailed=0

--- PedlarRun.f01 (steady flow) ---

Flow Title=NFF Regression Equation
Program Version=4.10
Number of Profiles= 1
Profile Names=P100yr
River Rch & RM=PedlarRun,Main            ,12901
     456
River Rch & RM=PedlarRun,Main            ,10486.1
     677
River Rch & RM=PedlarRun,Main            ,8735.6
     734
River Rch & RM=PedlarRun,Main            ,8422.4
     796
River Rch & RM=PedlarRun,Main            ,7080.8
     821
River Rch & RM=PedlarRun,Main            ,6783.2
    1099
River Rch & RM=PedlarRun,Main            ,4197.7
    1167
River Rch & RM=PedlarRun,Main            ,3037.9
    1276
River Rch & RM=PedlarRun,Main            ,3037.9
    1269
River Rch & RM=PedlarRun,Main            ,2561.6
    1354
River Rch & RM=PedlarRun,Main            ,93.2
    1401
Boundary for River Rch & Prof#=PedlarRun,Main            , 1
Up Type= 0
Dn Type= 3
Dn Slope=0.00464
DSS Import GetInterval= 0
DSS Import GetPeak= 0
DSS Import FillOption= 0

--- PedlarRun.g01 (geometry) ---

Geom Title=USGS 10m DEM
Program Version=4.10

River Reach=PedlarRun       ,Main
Reach XY= 30
     1791151.718      421189.803     1791766.502      421314.686
     1792206.053      421697.894     1792508.884      421855.299
     1792786.862      421887.429     1793198.908      422533.485
     1793464.454      422731.999     1793648.305       423054.79
     1793783.672      423565.561     1793614.135      423781.553
     1793679.067      423961.573     1793681.866      424519.991
     1793590.803      425392.034     1794017.714      426074.679
     1793973.508      426479.982     1794057.658      426423.528
     1794121.569      426705.269     1794567.456      427336.285
     1794643.084      427594.593     1794542.424      427793.783
     1794707.528      427873.672     1794925.359      428127.932
     1795269.307      428683.639     1795723.183      429154.771
     1795947.831      429592.349     1796522.179      430196.629
     1796747.466      430253.084     1796926.843      430417.656
     1797049.233      430389.428      1797099.19      430535.572

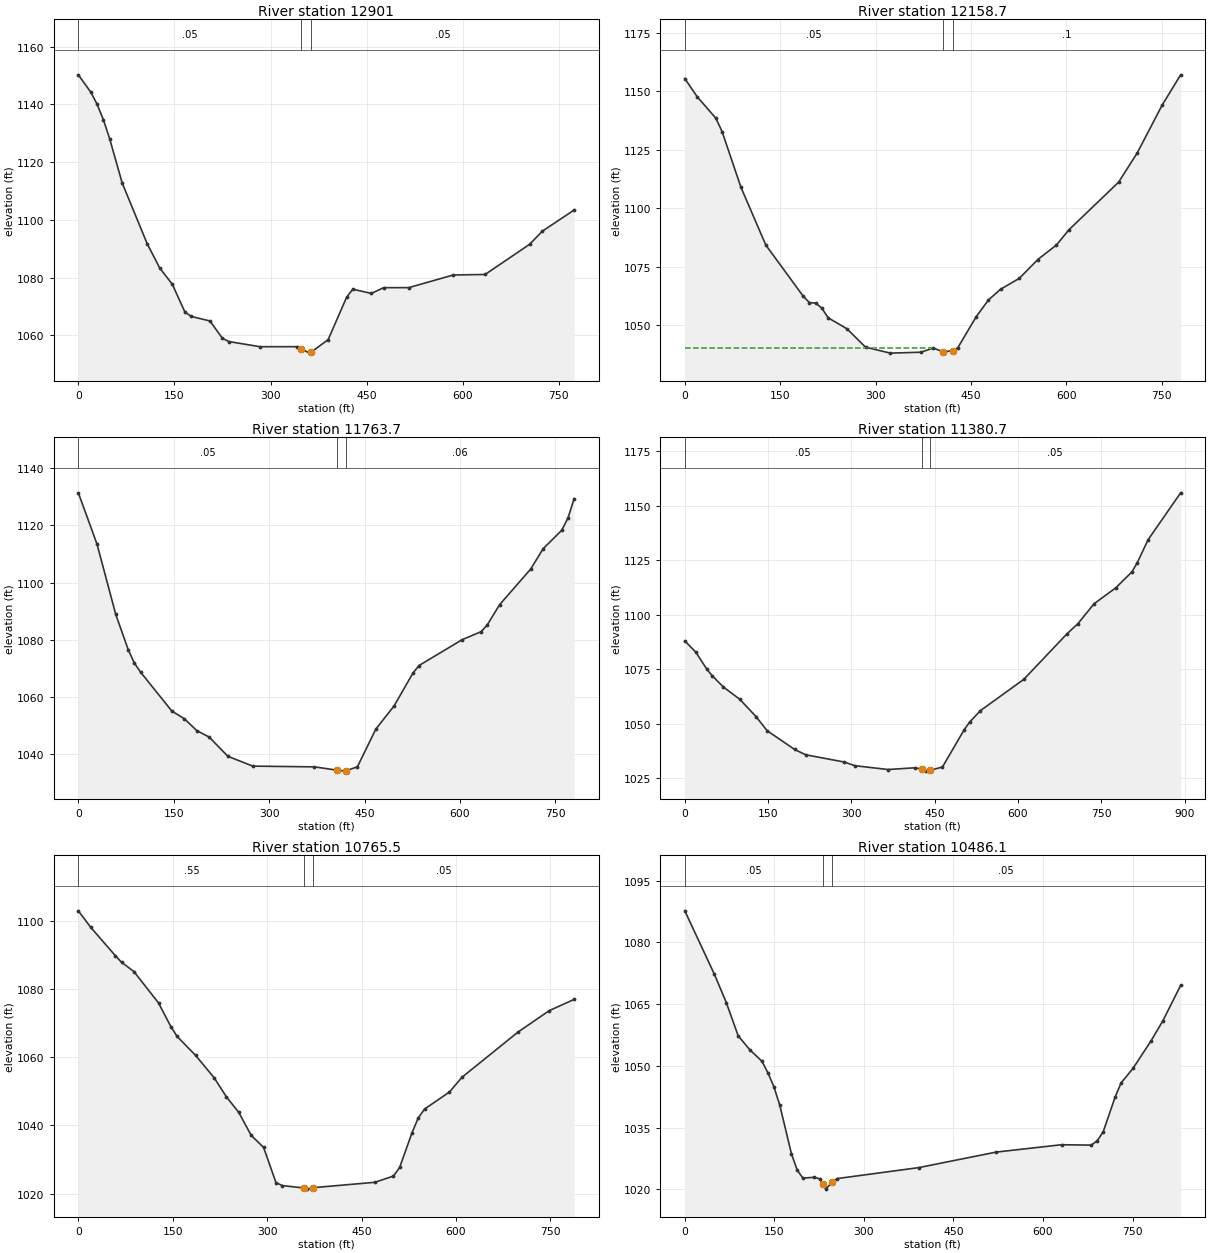
Type RM Length L Ch R = 1 ,12901   ,741.6,742.3,741.5
XS GIS Cut Line= 4
     1791066.735      421441.568     1791281.579      421226.724
     1791394.426      421070.474     1791559.357      420840.439
#Sta/Elev= 30
       0 1150.24    19.6 1144.19    29.3 1140.05    39.1 1134.71    48.9  1128.1
    68.4 1112.81   107.6 1091.68   127.1 1083.32   146.7  1077.7   166.2 1068.16
     176 1066.58   205.4    1065   224.9    1059   234.7 1057.88   283.6 1056.08
   341.7  1056.1   348.3 1055.28     361 1053.86   363.3  1054.2   389.9 1058.52
   418.8 1073.23   428.4    1076   457.3 1074.54   476.6 1076.53   515.7 1076.54
   585.2 1080.92   634.9  1081.1   704.4 1091.55   724.3 1096.09   773.9 1103.44
#Mann= 3 , 0 , 0
       0     .05       0   348.3    .045       0   363.3     .05       0
Bank Sta=348.3,363.3
XS Rating Curve= 0 ,0
Exp/Cntr=0.3,0.1

Type RM Length L Ch R = 1 ,12158.7 ,387.6,395,394.2
XS GIS Cut Line= 4
     1791657.013      421764.484     1791871.857      421549.641
     1791984.704      421393.391     1792149.635      421163.356
#Sta/Elev= 30
       0 1155.44    19.6 1147.63      49 1138.43    58.8 1132.64    88.2 1108.98
   127.4 1084.21   186.2 1062.33     196 1059.57   205.8  1059.4   215.6 1057.19
   225.4 1053.08   254.8 1048.43   284.2 1040.53   323.1 1037.98   371.3 1038.37
   390.6 1040.16   406.6 1038.51   421.6 1039.09   429.1 1040.22     458 1053.47
   477.3 1060.69   496.6 1065.33   525.9 1069.96   555.1 1078.03   584.4 1084.25
   603.9 1090.73     682 1111.09   711.3 1123.57   750.3 1143.97   779.6 1157.04
#Mann= 3 , 0 , 0
       0     .05       0   406.6    .045       0   421.6      .1       0
#XS Ineff= 2 , 0
          390.31 1040.15
Permanent Ineff=
       F       F
Bank Sta=406.6,421.6
XS Rating Curve= 0 ,0
Exp/Cntr=0.3,0.1

Type RM Length L Ch R = 1 ,11763.7 ,377.4,383,379.3
XS GIS Cut Line= 4
      1791926.11      421998.859     1792140.954      421784.016
     1792253.801      421627.766     1792418.732      421397.731
#Sta/Elev= 30
       0 1131.42    29.4 1113.47    58.8 1088.94    78.4 1076.62    88.2 1071.86
      98 1068.71     147 1055.14   166.6 1052.46   186.2 1048.32   205.8 1046.03
   235.2 1039.31   274.4 1035.89   371.3 1035.63  407.43 1034.45   419.5 1034.14
  420.95 1034.27   438.8 1035.66   467.7 1048.81   496.6 1056.98   525.9 1068.34
   535.6 1071.05   603.9 1080.14   633.2 1082.87     643 1085.26   662.5 1092.36
   711.3 1104.79   730.8 1111.88   760.1 1118.34   769.9 1122.63   779.6 1129.38
#Mann= 3 , 0 , 0
       0     .05       0  407.43    .045       0  420.95     .06       0
Bank Sta=407.43,420.95
XS Rating Curve= 0 ,0
Exp/Cntr=0.3,0.1

Type RM Length L Ch R = 1 ,11380.7 ,613.4,615.2,611
XS GIS Cut Line= 4
     1792245.121      422200.682     1792483.836      421872.991
      1792548.94      421775.335      1792698.68      421436.793
#Sta/Elev= 30
       0 1087.99    19.8 1082.84    39.6 1075.03    49.4 1071.98    69.2 1066.89
    98.9 1061.22   128.6 1053.16   148.3 1046.77   197.8 1038.17   217.5 1035.74
   286.8 1032.41   306.5 1030.71   365.9 1028.96   415.2 1029.77   426.4 1029.05
   434.8 1028.22   441.4 1028.55   464.1 1030.13   503.2 1047.22     513 1050.72
   532.5    1056   610.5 1070.33   688.4 1091.27   707.9 1095.87   737.1 1105.02
   776.1 1112.33   805.3 1119.66     815 1123.94   834.5 1134.46     893 1155.95
#Mann= 3 , 0 , 0
       0     .05       0   426.4    .045       0   441.4     .05       0
Bank Sta=426.4,441.4
XS Rating Curve= 0 ,0
Exp/Cntr=0.3,0.1

Type RM Length L Ch R = 1 ,10765.5 ,269.3,279.4,284.6
XS GIS Cut Line= 4
     1792797.977      422446.351      1792906.05      422226.299
     1793037.561       421995.83     1793208.568      421777.514
#Sta/Elev= 30
       0 1102.85    19.6 1098.04    58.8 1089.72    68.6 1087.79    88.3 1085.07
   127.5 1075.85   147.1 1068.91   156.9 1066.08   186.3 1060.52   215.7 1053.99
   235.4 1048.35     255  1043.8   274.6  1037.1   294.3 1033.58     314 1023.29
   323.8  1022.4   359.3 1021.66   363.1 1021.35   372.9 1021.77   471.2 1023.35
   500.7 1025.18   510.5 1027.69   530.3 1037.92   540.2 1042.24   550.1 1044.79
   589.7  1049.8   609.6 1054.11   698.7 1067.36   748.2 1073.62   787.8 1076.92
#Mann= 3 , 0 , 0
       0     .55       0   359.3    .045       0   372.9     .05       0
Bank Sta=359.3,372.9
XS Rating Curve= 0 ,0
Exp/Cntr=0.3,0.1

Type RM Length L Ch R = 1 ,10486.1 ,38.8,38.3,37.7
XS GIS Cut Line= 4
     1792932.526      422502.775     1793058.394      422389.927
     1793191.084      422264.258     1793556.441      421954.815
#Sta/Elev= 30
       0 1087.67    49.7 1072.23    69.6 1065.36    89.5  1057.3   109.4 1053.85
   129.3 1051.14   139.2 1048.34   149.2 1044.98   159.1 1040.47   178.7 1028.66
   188.3 1024.71   197.9 1022.76   217.1 1022.97   226.8 1022.54   231.5 1021.34
   236.4 1020.09   246.5 1021.81   255.6 1022.66   391.7 1025.31   521.4 1029.08
   631.1 1030.87     681 1030.78     691 1031.85   700.9 1034.02   720.9 1042.45
   730.8 1045.86   750.8 1049.41   780.7 1056.01   800.7 1060.93   830.6 1069.56
#Mann= 3 , 0 , 0
       0     .05       0   231.5    .045       0   246.5     .05       0
Bank Sta=231.5,246.5
XS Rating Curve= 0 ,0
Exp/Cntr=0.3,0.1

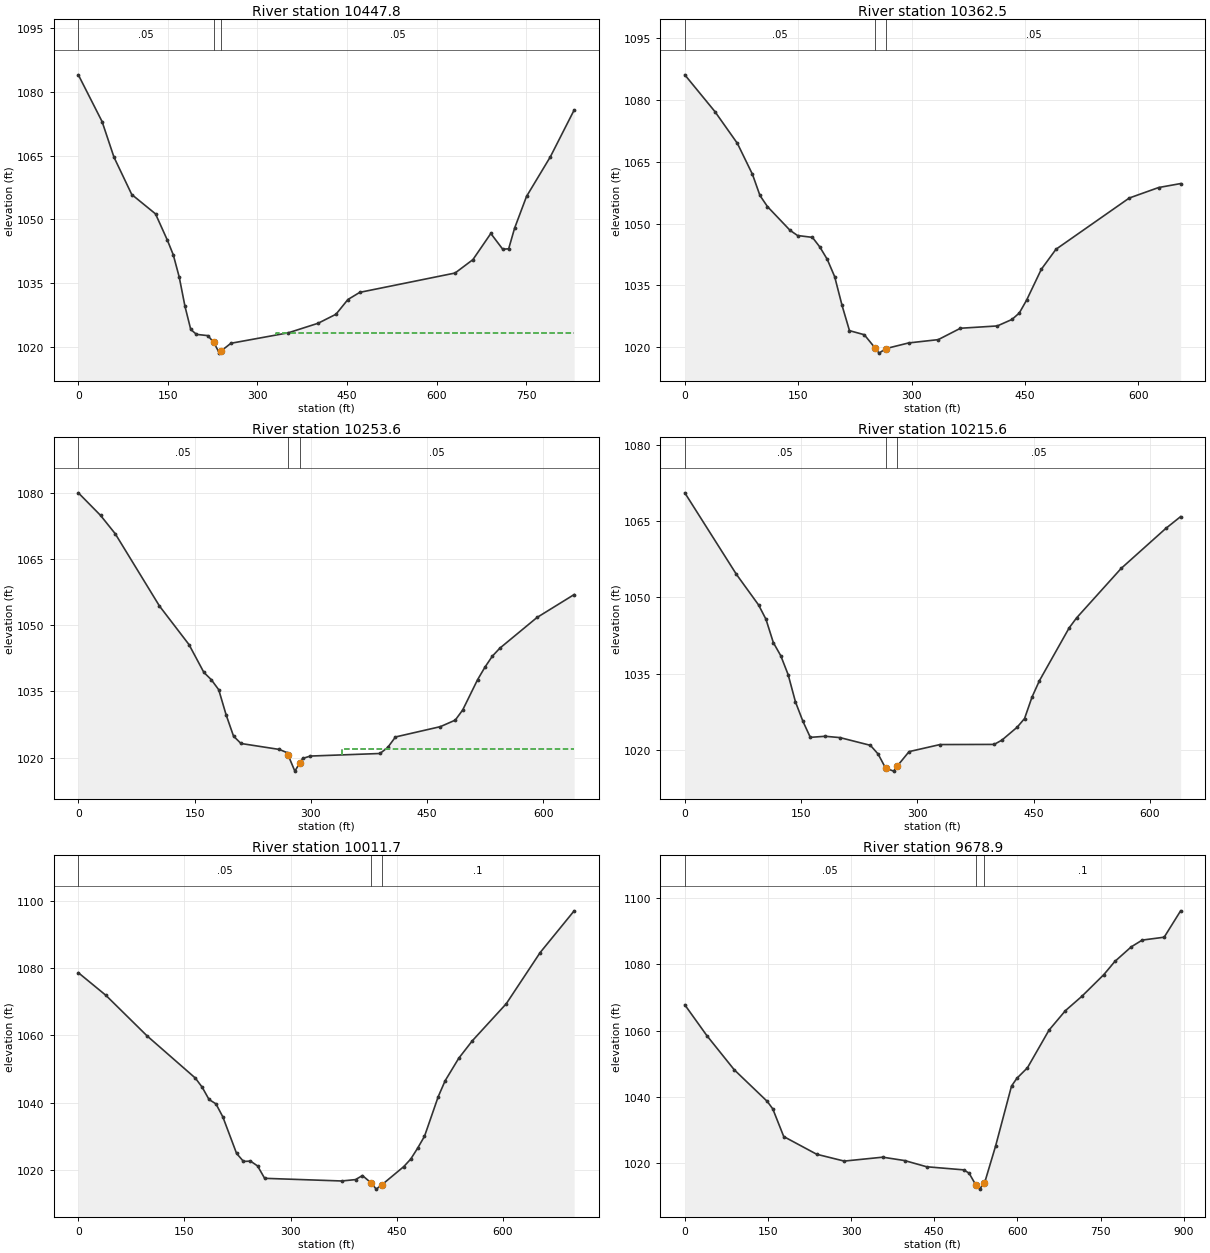
Type RM Length L Ch R = 1 ,10447.8 ,83.4,85.4,86.7
XS GIS Cut Line= 4
     1792953.142      422532.072      1793079.01      422419.224
     1793211.701      422293.555     1793577.057      421984.111
#Sta/Elev= 30
       0 1084.02    39.8    1073    59.7 1064.62    89.5 1055.82   129.3 1051.26
   149.2 1045.05   159.1 1041.59     169 1036.38   178.7 1029.44   188.3 1024.04
   197.9 1022.87   217.1 1022.57   226.8 1020.96   236.4 1018.45   238.9 1018.93
   255.6 1020.77   351.8 1023.24   401.7 1025.49   431.6 1027.61   451.6 1031.08
   471.5 1032.77   631.1 1037.32     661 1040.48     691 1046.64   710.9 1042.94
   720.9 1043.03   730.8 1047.88   750.8 1055.37   790.7  1064.7   830.6 1075.73
#Mann= 3 , 0 , 0
       0     .05       0   226.8    .045       0   238.9     .05       0
#XS Ineff= 2 , 0
                          331.87         1023.21
Permanent Ineff=
       F       F
Bank Sta=226.8,238.9
XS Rating Curve= 0 ,0
Exp/Cntr=0.3,0.1

Type RM Length L Ch R = 1 ,10362.5 ,119.2,108.9,98.9
XS GIS Cut Line= 4
     1792983.741      422640.144     1793085.304      422517.749
     1793254.575      422369.311     1793443.377      422173.999
#Sta/Elev= 30
       0 1086.04    39.8 1077.14    69.6 1069.41    89.5 1061.92    99.4 1056.79
   109.3 1054.11   139.2 1048.35   149.1 1047.09   168.8 1046.64   178.6 1044.31
   188.4 1041.32   198.2 1037.13     208 1030.14   217.8 1024.03   237.4 1023.04
   251.2 1019.94   256.9 1018.58   266.2 1019.69   296.1 1021.05   335.2 1021.85
   364.6 1024.61   413.3 1025.17   432.7 1026.74   442.4  1028.3   452.1 1031.43
   471.5 1038.89   490.9 1043.75   587.9 1056.18   626.7 1058.72   655.8 1059.68
#Mann= 3 , 0 , 0
       0     .05       0   251.2    .045       0   266.2     .05       0
Bank Sta=251.2,266.2
XS Rating Curve= 0 ,0
Exp/Cntr=0.3,0.1

Type RM Length L Ch R = 1 ,10253.6 ,37.7,37.9,37.7
XS GIS Cut Line= 5
     1793048.845      422766.447     1793146.502       422662.28
     1793190.772       422599.78     1793266.622      422415.019
     1793397.804      422237.801
#Sta/Elev= 30
       0 1080.06    28.6 1074.95    47.6 1070.78   104.7 1054.37   142.8 1045.62
   161.9 1039.33   171.5 1037.67   181.1 1035.39   190.6 1029.71   200.2 1024.86
   209.8 1023.19   259.3 1021.84   269.3 1021.11   270.7 1020.52   279.3 1016.92
   285.7 1018.76   289.3 1019.79   299.3 1020.34   389.1 1020.92   399.1 1022.29
   409.1 1024.67     467 1027.01   486.2 1028.49   495.8 1030.79     515 1037.66
   524.6 1040.53   534.1 1043.01   543.7 1044.81   591.7 1051.78   639.6 1056.98
#Mann= 3 , 0 , 0
       0     .05       0   270.7    .045       0   285.7     .05       0
#XS Ineff= 2 , 0
                          340.22         1022.03
Permanent Ineff=
       F       F
Bank Sta=270.7,285.7
XS Rating Curve= 0 ,0
Exp/Cntr=0.3,0.1

Type RM Length L Ch R = 1 ,10215.6 ,191.3,203.9,215.6
XS GIS Cut Line= 5
     1793087.908      422770.353     1793185.564      422666.186
     1793229.835      422603.686     1793305.684      422418.925
     1793436.866      422241.707
#Sta/Elev= 30
       0 1070.59    66.6 1054.54    95.2 1048.51   104.7  1045.7   114.2 1041.11
   123.8 1038.52   133.3  1034.8   142.8 1029.41   152.4  1025.6   161.9 1022.45
   181.1 1022.66   200.2  1022.4   239.4 1020.88   249.3 1019.18     259 1016.41
   269.3  1015.8     274 1016.79   289.3 1019.64   329.2 1021.03   399.1 1021.06
   409.1 1021.91   428.7 1024.44   438.3 1026.16   447.9 1030.38   457.4 1033.59
   495.8    1044   505.4 1045.97   562.9 1055.71   620.4 1063.57   639.6 1065.91
#Mann= 3 , 0 , 0
       0     .05       0     259    .045       0     274     .05       0
Bank Sta=259,274
XS Rating Curve= 0 ,0
Exp/Cntr=0.3,0.1

Type RM Length L Ch R = 1 ,10011.7 ,331,332.8,334.7
XS GIS Cut Line= 5
      1793051.45      422895.353     1793250.112      422772.939
     1793347.551      422722.601      1793488.61      422618.434
     1793635.095      422509.927
#Sta/Elev= 30
       0 1078.59    38.9 1071.88    97.2 1059.81   165.3  1047.3     175 1044.58
   184.7 1040.93   194.5 1039.62   204.2 1035.77   223.6 1024.92   233.4 1022.53
   243.3 1022.62   253.3 1021.19   263.3 1017.51   372.2 1016.72   391.7 1017.13
   401.5 1018.33   413.5 1016.21     421  1014.3   428.5 1015.51   459.9 1020.99
   469.7 1023.22   479.4 1026.43   489.2    1030   508.6 1041.77   518.4 1046.51
   537.6 1053.18   556.8 1058.37   604.7 1069.36   652.7 1084.59   700.7 1096.97
#Mann= 3 , 0 , 0
       0     .05       0   413.5    .045       0   428.5      .1       0
Bank Sta=413.5,428.5
XS Rating Curve= 0 ,0
Exp/Cntr=0.3,0.1

Type RM Length L Ch R = 1 ,9678.9  ,927,943.3,955.7
XS GIS Cut Line= 4
     1793166.258      423295.971     1793489.175      423002.568
      1793661.05      422898.402     1793895.425      422792.499
#Sta/Elev= 30
       0 1067.75    39.7 1058.48    89.2 1048.15   148.7 1038.62   158.7 1036.36
   178.5    1028     238 1022.66   287.6  1020.6     357 1021.78   396.6 1020.76
   436.3 1018.89   503.3 1017.95   512.9 1016.95   524.9 1013.43     532 1012.14
   539.9 1014.05   541.6 1014.46   560.7 1025.14   589.4 1043.23     599 1045.57
   618.1 1048.74   657.1 1060.12   686.7    1066   716.4 1070.33     756 1076.87
   775.8 1080.83   805.4 1085.24   825.2 1087.28   864.8 1088.15   894.5 1096.11
#Mann= 3 , 0 , 0
       0     .05       0   524.9    .045       0   539.9      .1       0
Bank Sta=524.9,539.9
XS Rating Curve= 0 ,0
Exp/Cntr=0.3,0.1

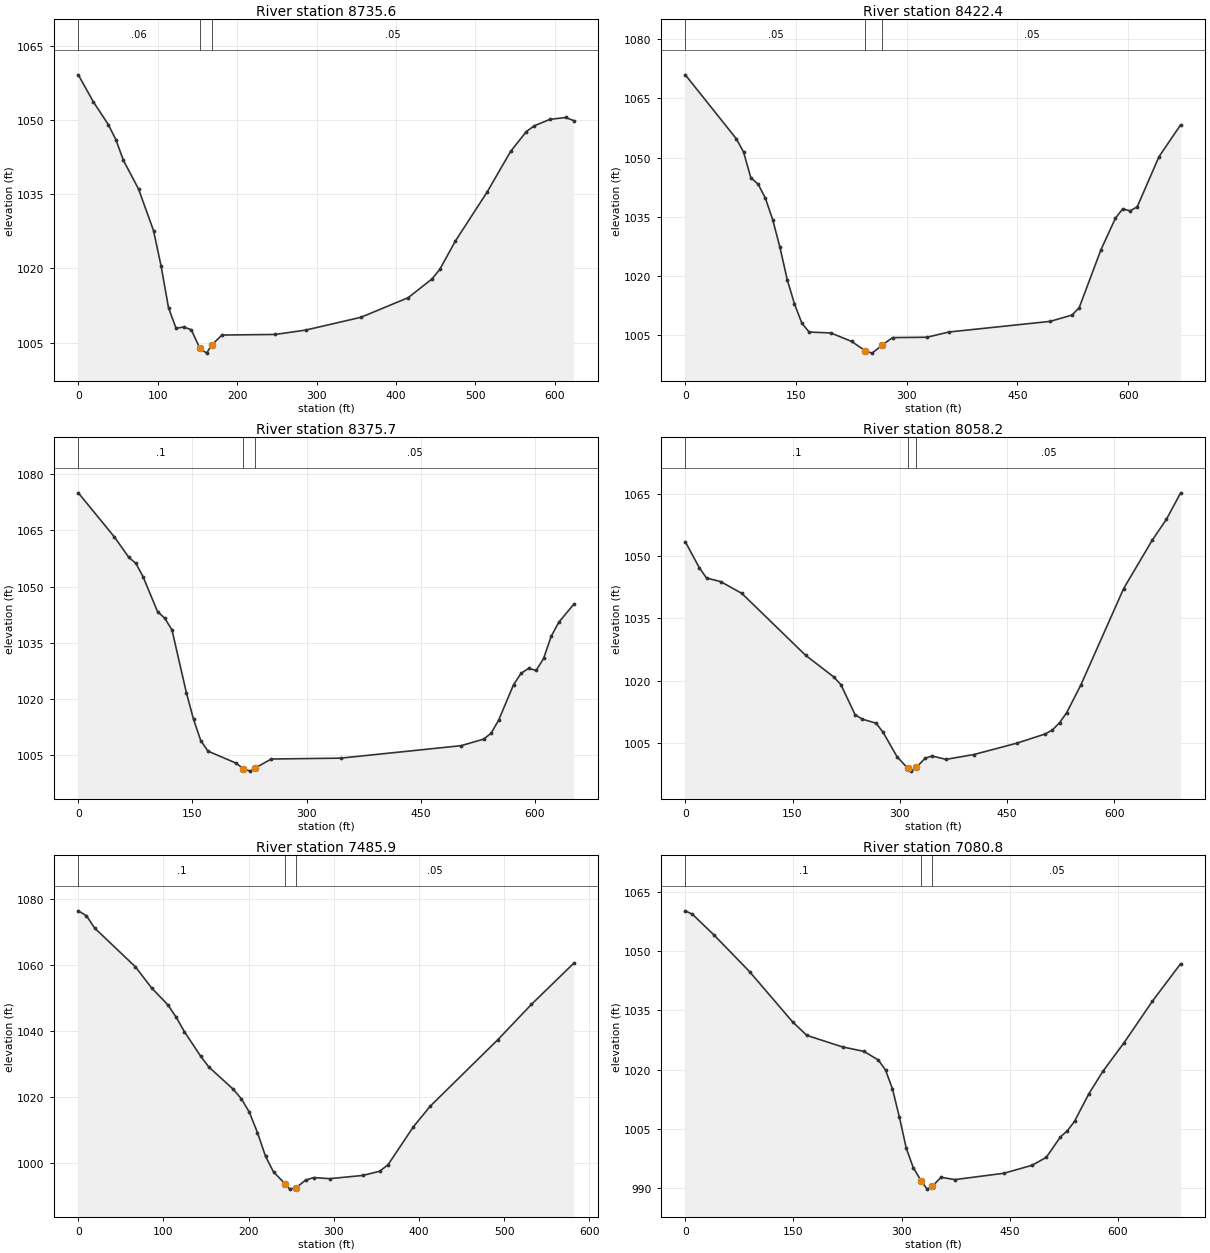
Type RM Length L Ch R = 1 ,8735.6  ,263.4,313.2,342.9
XS GIS Cut Line= 4
     1793457.056      423757.945     1793579.452      423770.966
     1793742.213      423783.987     1794079.452      423782.685
#Sta/Elev= 30
       0 1059.16    18.9 1053.71    37.9 1049.06    47.3 1046.04    56.8 1041.85
    75.8 1036.07    94.7 1027.64   104.2  1020.5   113.6    1012   123.1 1007.87
   132.7 1008.14   142.3 1007.57   152.9 1003.86   161.5 1002.85   167.9 1004.47
   180.7 1006.51     248 1006.63   286.4 1007.52   355.8  1010.1   415.3 1014.07
   445.1 1017.84     455 1019.78   474.8 1025.56   514.5  1035.4   544.3 1043.68
   564.1 1047.69     574 1048.85   593.8 1050.15   613.7 1050.53   623.6  1049.9
#Mann= 3 , 0 , 0
       0     .06       0   152.9    .045       0   167.9     .05       0
Bank Sta=152.9,167.9
XS Rating Curve= 0 ,0
Exp/Cntr=0.3,0.1

Type RM Length L Ch R = 1 ,8422.4  ,68.3,46.7,48.5
XS GIS Cut Line= 4
     1793474.504      423899.901     1793643.775      424019.259
     1793677.412       424124.51     1794022.595      424201.324
#Sta/Elev= 30
       0 1070.96      69 1054.81    78.9 1051.43    88.8 1044.91    98.6 1043.31
   108.5 1039.74   118.4  1034.3   128.2 1027.33   138.1 1019.13   147.9 1012.99
   157.8 1008.15   167.7 1005.85   197.3 1005.61   225.5 1003.46     244 1001.09
   253.2 1000.51   266.6 1002.53   280.8 1004.44   327.4 1004.53   356.9 1005.85
   494.4 1008.55   523.9 1010.14   533.7    1012   563.2 1026.68   582.8 1034.65
   592.7 1037.04   602.5 1036.53   612.3 1037.53   641.8 1050.22   671.2 1058.31
#Mann= 3 , 0 , 0
       0     .05       0     244    .045       0   266.6     .05       0
Bank Sta=244,266.6
XS Rating Curve= 0 ,0
Exp/Cntr=0.3,0.1

Type RM Length L Ch R = 1 ,8375.7  ,344,317.5,281.7
XS GIS Cut Line= 5
     1793460.398      423949.814     1793605.798       424038.79
     1793637.265      424135.361      1793663.22      424170.074
     1793987.438      424257.314
#Sta/Elev= 30
       0 1075.05    47.4 1063.28    66.3 1057.85    75.8 1056.19    85.2 1052.61
   104.2 1043.32   113.6 1041.59   123.1 1038.46     142 1021.74   151.5 1014.56
     161 1008.87   170.5 1006.08   207.4 1002.89   216.6 1001.42   225.9 1000.75
   232.5 1001.58   253.6 1003.98     345 1004.22     503 1007.54   532.6 1009.28
   542.5 1010.84   552.4 1014.31   572.1 1023.82     582 1026.86   591.9  1028.2
   601.8 1027.63   611.6 1030.83   621.5 1036.71   631.4 1040.46   651.1 1045.28
#Mann= 3 , 0 , 0
       0      .1       0   216.6    .045       0   232.5     .05       0
Bank Sta=216.6,232.5
XS Rating Curve= 0 ,0
Exp/Cntr=0.3,0.1

Type RM Length L Ch R = 1 ,8058.2  ,570.7,572.3,572.2
XS GIS Cut Line= 4
     1793347.551      424377.332     1793604.713      424377.332
     1793741.431      424377.332     1794039.956      424392.296
#Sta/Elev= 30
       0 1053.45    19.8 1047.14    29.7 1044.72    49.5 1043.86    79.1 1041.02
   168.2 1026.14   207.7 1020.91   217.6 1019.09   237.4 1011.86   247.3 1010.78
   266.9 1009.79   276.7 1007.58   296.2 1001.72   310.8  999.01   315.8  998.26
  323.15  999.16   335.3 1001.35     345 1001.91   364.6 1001.09   403.8 1002.26
   463.6 1004.98   503.5 1007.21   513.4 1008.16   523.4  1009.9   533.4 1012.33
   553.3 1019.03   613.1  1042.2   652.9 1053.79   672.8 1058.83   692.8 1065.22
#Mann= 3 , 0 , 0
       0      .1       0   310.8    .045       0  323.15     .05       0
Bank Sta=310.8,323.15
XS Rating Curve= 0 ,0
Exp/Cntr=0.3,0.1

Type RM Length L Ch R = 1 ,7485.9  ,406.4,405.2,403.2
XS GIS Cut Line= 4
     1793377.933      424923.121     1793568.905      424938.312
     1793691.518      424942.653     1793958.445      424960.014
#Sta/Elev= 30
       0 1076.32     9.6 1074.82    19.2  1071.1      67  1059.4    86.2 1052.96
   105.4 1047.82     115 1044.09   124.5  1039.8   143.7 1032.33   153.3 1029.07
     182 1022.32   191.6  1019.4     201 1015.32   210.4 1009.22   219.9 1002.04
   229.3   997.3  243.28   993.6   248.2   992.1     256  992.56   267.1  994.86
   276.5   995.6   295.4  995.27   334.1  996.24   353.9  997.51   363.8  999.49
   393.5 1010.95   413.3 1017.19   492.6 1037.28   532.2 1048.01   581.8 1060.43
#Mann= 3 , 0 , 0
       0      .1       0  243.28    .045       0     256     .05       0
Bank Sta=243.28,256
XS Rating Curve= 0 ,0
Exp/Cntr=0.3,0.1

Type RM Length L Ch R = 1 ,7080.8  ,114.4,116.7,118.5
XS GIS Cut Line= 4
      1793246.64      425341.958     1793524.418      425341.958
     1793658.966      425336.533     1793925.893      425271.429
#Sta/Elev= 30
       0 1060.21     9.9 1059.34    39.7 1054.12    89.3  1044.8   148.8 1032.13
   168.6 1028.71   218.2 1025.78     248 1024.66   267.9 1022.45   277.8 1019.94
   287.4 1015.18     297 1008.04   306.6 1000.13   316.2  995.29   327.6   991.8
   335.5  989.82   342.6  990.51   354.7  992.82     374  992.23   441.9  993.83
   481.1  995.85   500.8  997.86   520.4 1003.02   530.2 1004.62     540 1006.98
   559.6 1013.86   579.2 1019.59   608.7 1026.85   647.9 1037.33   687.2 1046.84
#Mann= 3 , 0 , 0
       0      .1       0   327.6    .045       0   342.6     .05       0
Bank Sta=327.6,342.6
XS Rating Curve= 0 ,0
Exp/Cntr=0.3,0.1

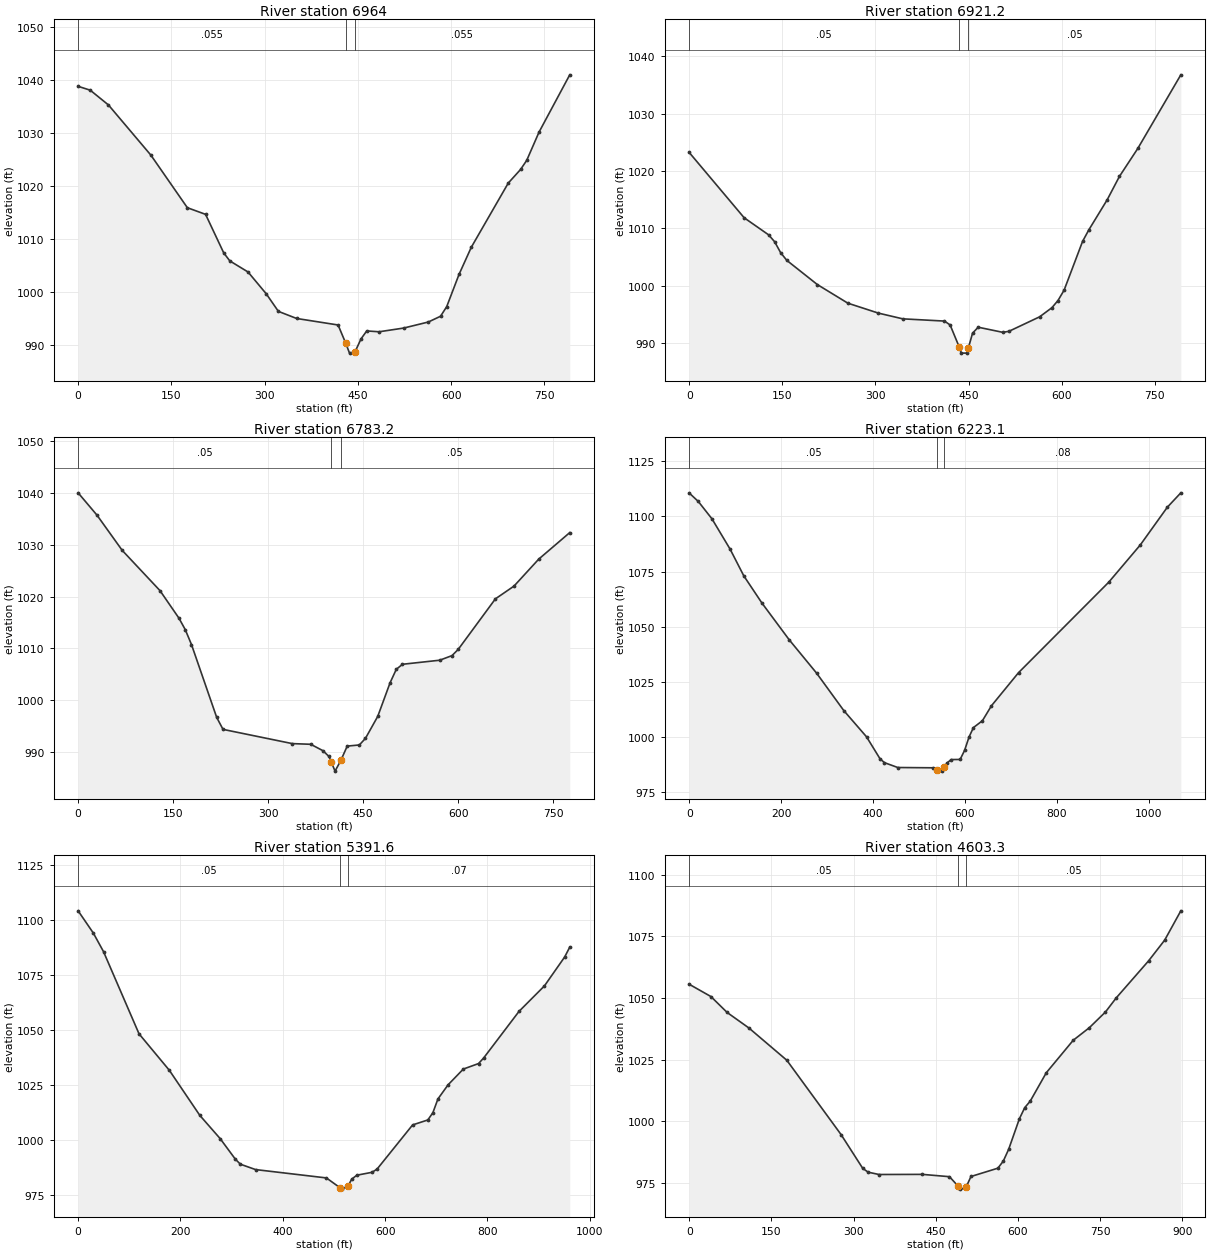
Type RM Length L Ch R = 1 ,6964    ,44.9,42.8,40.5
XS GIS Cut Line= 4
     1793167.864       425461.75     1793558.142      425451.377
     1793631.839      425454.806     1793950.633      425384.059
#Sta/Elev= 30
       0 1038.78    19.5 1038.05    48.8 1035.26   117.1 1025.78   175.7 1015.87
     205 1014.62   234.2 1007.34     244 1005.83   273.3 1003.74   302.6  999.62
   322.1  996.31   351.4  994.97   418.1  993.74   430.4   990.3   436.5  988.43
   445.4  988.68     455  991.12   464.2  992.62     484  992.46   523.6  993.16
   563.2   994.3   582.9  995.39   592.8   997.2   612.6 1003.28   632.4 1008.42
   691.8 1020.52   711.6 1023.09   721.5 1024.81   741.3 1030.14   790.7 1040.95
#Mann= 3 , 0 , 0
       0    .055       0   430.4    .045       0   445.4    .055       0
Bank Sta=430.4,445.4
XS Rating Curve= 0 ,0
Exp/Cntr=0.3,0.1

Type RM Length L Ch R = 1 ,6921.2  ,149.4,138,126.5
XS GIS Cut Line= 4
     1793171.336      425495.778     1793564.485      425497.798
     1793636.707      425494.326     1793954.105      425418.087
#Sta/Elev= 30
       0 1023.25    88.5 1011.86   127.8 1008.89   137.6 1007.68   147.4 1005.75
   157.3 1004.42   206.4 1000.21   255.6  996.96   304.7  995.23     344  994.23
   411.2  993.84   420.3  993.16   434.8  989.35   438.4  988.25   447.4  988.26
   449.8  989.19   456.4  991.73   465.5  992.77     505  991.88   514.9  992.05
   564.4  994.58   584.2  996.17     594  997.42   603.9  999.24   633.6 1007.73
   643.5 1009.71   673.2 1014.98     693 1019.07   722.6 1023.95   791.9 1036.79
#Mann= 3 , 0 , 0
       0     .05       0   434.8    .045       0   449.8     .05       0
Bank Sta=434.8,449.8
XS Rating Curve= 0 ,0
Exp/Cntr=0.3,0.1

Type RM Length L Ch R = 1 ,6783.2  ,557,560.1,562.9
XS GIS Cut Line= 4
     1793376.544      425829.415     1793655.407      425621.082
     1793755.234      425563.573     1794066.648      425532.106
#Sta/Elev= 30
       0 1039.98    29.8 1035.68    69.6  1028.9   129.3 1021.14   159.1 1015.86
   169.1 1013.65     179 1010.76   218.8  996.73   228.8  994.42   338.2  991.68
   367.3  991.55   386.5  990.32   396.1   989.2   399.8  988.11   405.7  986.38
   414.8  988.43   424.9   991.2   444.1  991.42   453.7  992.69   473.1  996.92
   492.6  1003.4   502.4 1005.99   512.2 1006.96   570.9 1007.74   590.4 1008.63
   600.2 1009.83   658.9 1019.56   688.3 1022.02   727.4 1027.22   776.3 1032.32
#Mann= 3 , 0 , 0
       0     .05       0   399.8    .045       0   414.8     .05       0
Bank Sta=399.8,414.8
XS Rating Curve= 0 ,0
Exp/Cntr=0.3,0.1

Type RM Length L Ch R = 1 ,6223.1  ,750.8,831.5,810.6
XS GIS Cut Line= 4
     1793486.136      426223.597     1793868.081       426119.43
     1794082.925      426030.455      1794473.55      425824.292
#Sta/Elev= 30
       0 1110.65    19.8  1106.8    49.5 1098.94    89.1 1085.16   118.8 1073.09
   158.4 1060.72   217.7 1044.08   277.1 1029.02   336.5 1011.99     386 1000.09
   415.3  990.15     425  988.38     454  986.18   531.5  986.05   540.4  984.87
   550.9  984.54   555.4  986.21   560.6  988.14   570.3  989.78   589.7  989.83
   599.4  993.94   609.1 1000.01   618.7 1004.29   638.2 1007.39   657.9 1014.18
   716.8 1029.17   913.1 1070.18   981.8 1087.07  1040.7 1104.19  1070.1 1110.72
#Mann= 3 , 0 , 0
       0     .05       0   540.4    .045       0   555.4     .08       0
Bank Sta=540.4,555.4
XS Rating Curve= 0 ,0
Exp/Cntr=0.3,0.1

Type RM Length L Ch R = 1 ,5391.6  ,790.5,788.3,785.5
XS GIS Cut Line= 4
     1793616.562      426677.867      1793903.02      426653.561
     1794046.292      426615.716     1794536.701      426427.867
#Sta/Elev= 30
       0 1104.31    29.7 1094.19    49.6 1085.74     119 1048.32   178.4 1031.66
   237.9 1011.15   277.6 1000.59   307.2  991.25   317.1  988.94   346.8  986.49
   485.2  982.69   512.1  978.18   514.9  977.59   527.1   978.9   534.8  982.16
   544.7  983.93   574.4  985.25   584.3  986.73   653.7 1006.83   683.4 1009.08
   693.3 1012.38   703.2 1018.66     723 1025.08   752.8 1032.26   782.5 1034.76
   792.4 1037.26   861.7 1058.54   911.3 1070.12   950.9  1083.3   960.8 1087.78
#Mann= 3 , 0 , 0
       0     .05       0   512.1    .045       0   527.1     .07       0
Bank Sta=512.1,527.1
XS Rating Curve= 0 ,0
Exp/Cntr=0.3,0.1

Type RM Length L Ch R = 1 ,4603.3  ,401.1,405.6,413.3
XS GIS Cut Line= 3
     1794083.576      427462.589     1794486.065      427229.429
     1794864.826      427021.617
#Sta/Elev= 30
       0 1055.63    39.6 1050.65    69.3 1044.18   108.9 1037.91   178.1 1024.83
   277.1   994.7   316.7  980.99   326.6  979.44   346.4   978.5   425.6  978.55
     475  977.61   490.8  973.76   494.6  972.57   504.4  972.93   505.8  973.61
   514.2  977.69   563.3  981.06   573.2  983.93     583  988.72   602.6 1001.11
   612.4 1005.63   622.2 1008.19   651.7 1019.76   700.8 1032.92   730.2 1038.01
   759.7  1044.4   779.4 1050.13   838.3  1065.1   867.7 1073.51   897.2  1085.4
#Mann= 3 , 0 , 0
       0     .05       0   490.8    .045       0   505.8     .05       0
Bank Sta=490.8,505.8
XS Rating Curve= 0 ,0
Exp/Cntr=0.3,0.1

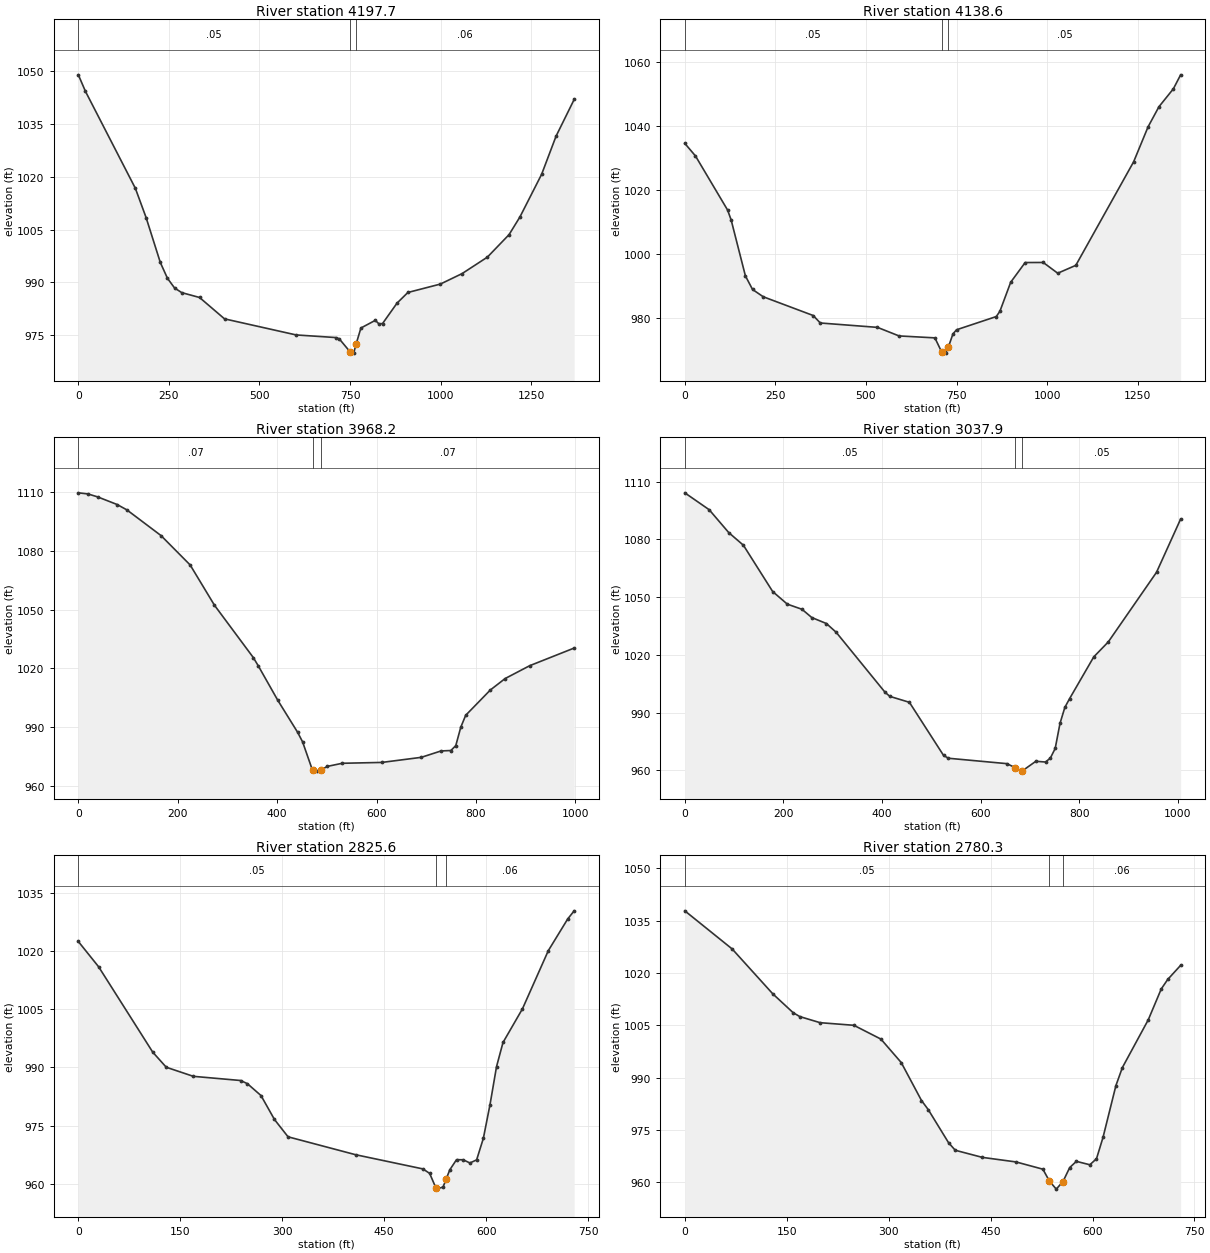
Type RM Length L Ch R = 1 ,4197.7  ,59.2,59.2,55.9
XS GIS Cut Line= 5
     1793885.659        427636.2     1794328.367      427625.784
     1794545.381      427610.159     1794722.464      427582.381
      1795246.77      427512.936
#Sta/Elev= 30
       0  1048.9    19.7  1044.2   157.4 1016.71     187 1008.42   226.3  995.67
     246  991.18   265.7  988.43   285.4  987.12   334.6  985.74   403.5  979.68
   601.1  975.12   710.2  974.38   720.2  974.01     750  970.33     760  969.96
   766.6  972.51   779.9  977.08   819.7  979.26   829.7  978.25   839.7  978.36
   879.6  984.14   909.5  987.16   999.3  989.55  1059.2  992.52    1129  997.19
  1188.9 1003.58  1218.9  1008.6  1278.7 1020.68  1318.6 1031.51  1368.5 1041.91
#Mann= 3 , 0 , 0
       0     .05       0     750    .045       0   766.6     .06       0
Bank Sta=750,766.6
XS Rating Curve= 0 ,0
Exp/Cntr=0.3,0.1

Type RM Length L Ch R = 1 ,4138.6  ,176.6,170.3,163.3
XS GIS Cut Line= 5
     1793892.169      427679.603     1794334.878      427669.186
     1794551.892      427653.561     1794728.975      427625.784
      1795253.28      427556.339
#Sta/Elev= 30
       0 1034.55    29.5 1030.61   118.1 1013.71   127.9 1010.62   167.3  993.12
     187  988.88   216.5   986.6   354.3  980.74     374   978.4   531.8  977.03
   591.2  974.36   690.3  973.75  708.68   969.4   710.2  968.98   720.2  969.14
   727.3  970.82   740.1  974.98     750  976.28   859.6  980.41   869.6  982.03
   899.5  991.14   939.4   997.3   989.3  997.32  1029.3  993.96  1079.2  996.42
  1238.8 1028.79  1278.7 1039.73  1308.7 1046.01  1348.6 1051.63  1368.5 1055.98
#Mann= 3 , 0 , 0
       0     .05       0  708.68    .045       0   727.3     .05       0
Bank Sta=708.68,727.3
XS Rating Curve= 0 ,0
Exp/Cntr=0.3,0.1

Type RM Length L Ch R = 1 ,3968.2  ,924.8,930.4,941.3
XS GIS Cut Line= 4
      1794142.82      428059.811     1794468.341      427842.797
     1794621.336      427748.396     1795039.088      427661.591
#Sta/Elev= 30
       0 1109.66    19.6 1109.08    39.1 1107.56    78.2 1103.67    97.8 1100.92
   166.3 1087.82     225 1072.78   273.9  1052.2   352.1 1025.43   361.9 1021.29
   401.2 1003.66   441.2  987.26   451.2  982.36   471.1  967.87   472.9  967.78
   481.1  967.38   487.9  967.94   501.1   969.8     531  971.39   610.7  971.83
   690.1  974.43   729.8  977.69   749.6  977.92   759.5  980.41   769.5  989.78
   779.4  995.91     829 1008.85   858.8 1014.71   908.4  1021.3   997.7  1030.3
#Mann= 3 , 0 , 0
       0     .07       0   472.9    .045       0   487.9     .07       0
Bank Sta=472.9,487.9
XS Rating Curve= 0 ,0
Exp/Cntr=0.3,0.1

Type RM Length L Ch R = 1 ,3037.9  ,213,212.2,206.6
XS GIS Cut Line= 3
      1794538.22      428715.844     1795120.296      428464.579
     1795460.095      428313.067
#Sta/Elev= 30
       0 1104.16    49.5 1095.38    89.2 1083.49   118.9 1076.94   178.3 1052.88
     208 1046.33   237.8 1043.66   257.6 1039.38   287.3 1036.26   307.1 1031.73
   406.2 1000.58   416.1  998.41   455.7  995.34     525  967.76   534.9  966.28
   653.6  963.47     670  961.43     683  959.59     685  959.76   712.3  964.71
   731.9  964.32   741.7  966.37   751.5  971.36   761.3  984.42   771.1   992.7
   780.8  997.28   829.8 1018.95   859.2  1026.7   957.1 1062.88    1006 1090.53
#Mann= 3 , 0 , 0
       0     .05       0     670    .045       0     685     .05       0
Bank Sta=670,685
XS Rating Curve= 0 ,0
Exp/Cntr=0.3,0.1

Type RM Length L Ch R = 1 ,2825.6  ,45.2,45.3,45.4
XS GIS Cut Line= 5
     1794868.081      429003.171     1795062.525      428763.587
     1795192.734      428655.948     1795310.789      428605.601
     1795425.372      428558.726
#Sta/Elev= 30
       0 1022.47    29.9 1015.94   109.5  993.93   129.4  990.04   169.2   987.7
   238.9  986.62   248.8   985.8   268.8  982.74   288.6  976.57   308.6   972.1
   407.9  967.49   507.1  963.82     517  962.66   526.1  958.94   526.9  958.61
   536.7  959.16   541.1  961.13   546.6  963.59   556.5   966.2   566.4  966.18
   576.2  965.35   586.1  966.16     596  971.72   605.8  980.42   615.4  990.22
   624.9  996.43   653.5  1005.1   691.6 1020.12   720.1 1028.28   729.6 1030.38
#Mann= 3 , 0 , 0
       0     .05       0   526.1    .045       0   541.1     .06       0
#XS Ineff= 2 , 0
                          556.94          966.19
Permanent Ineff=
       F       F
Bank Sta=526.1,541.1
XS Rating Curve= 0 ,0
Exp/Cntr=0.3,0.1

Type RM Length L Ch R = 1 ,2780.3  ,222.8,218.8,214.2
XS GIS Cut Line= 5
     1794876.761       429048.31     1795071.206      428808.726
     1795201.414      428701.087      1795319.47       428650.74
     1795434.053      428603.865
#Sta/Elev= 30
       0 1037.84    69.7  1026.9   129.4 1014.04   159.3 1008.64   169.2  1007.5
   199.1 1005.75   248.8    1005   288.6 1001.04   318.5  994.31   348.3  983.42
   358.2  980.82   388.1  971.32     398  969.15   437.8  967.11   487.4   965.8
   526.9  963.72   536.5  960.32   546.6     958   556.5  960.18   566.4  964.19
   576.2  965.97     596  964.99   605.8  966.71   615.4  972.84   634.4  987.72
   643.9  992.88     682 1006.58   701.1 1015.43   710.6 1018.15   729.6  1022.2
#Mann= 3 , 0 , 0
       0     .05       0   536.5    .045       0   556.5     .06       0
#XS Ineff= 2 , 0
                          576.18          965.95
Permanent Ineff=
       F       F
Bank Sta=536.5,556.5
XS Rating Curve= 0 ,0
Exp/Cntr=0.3,0.1