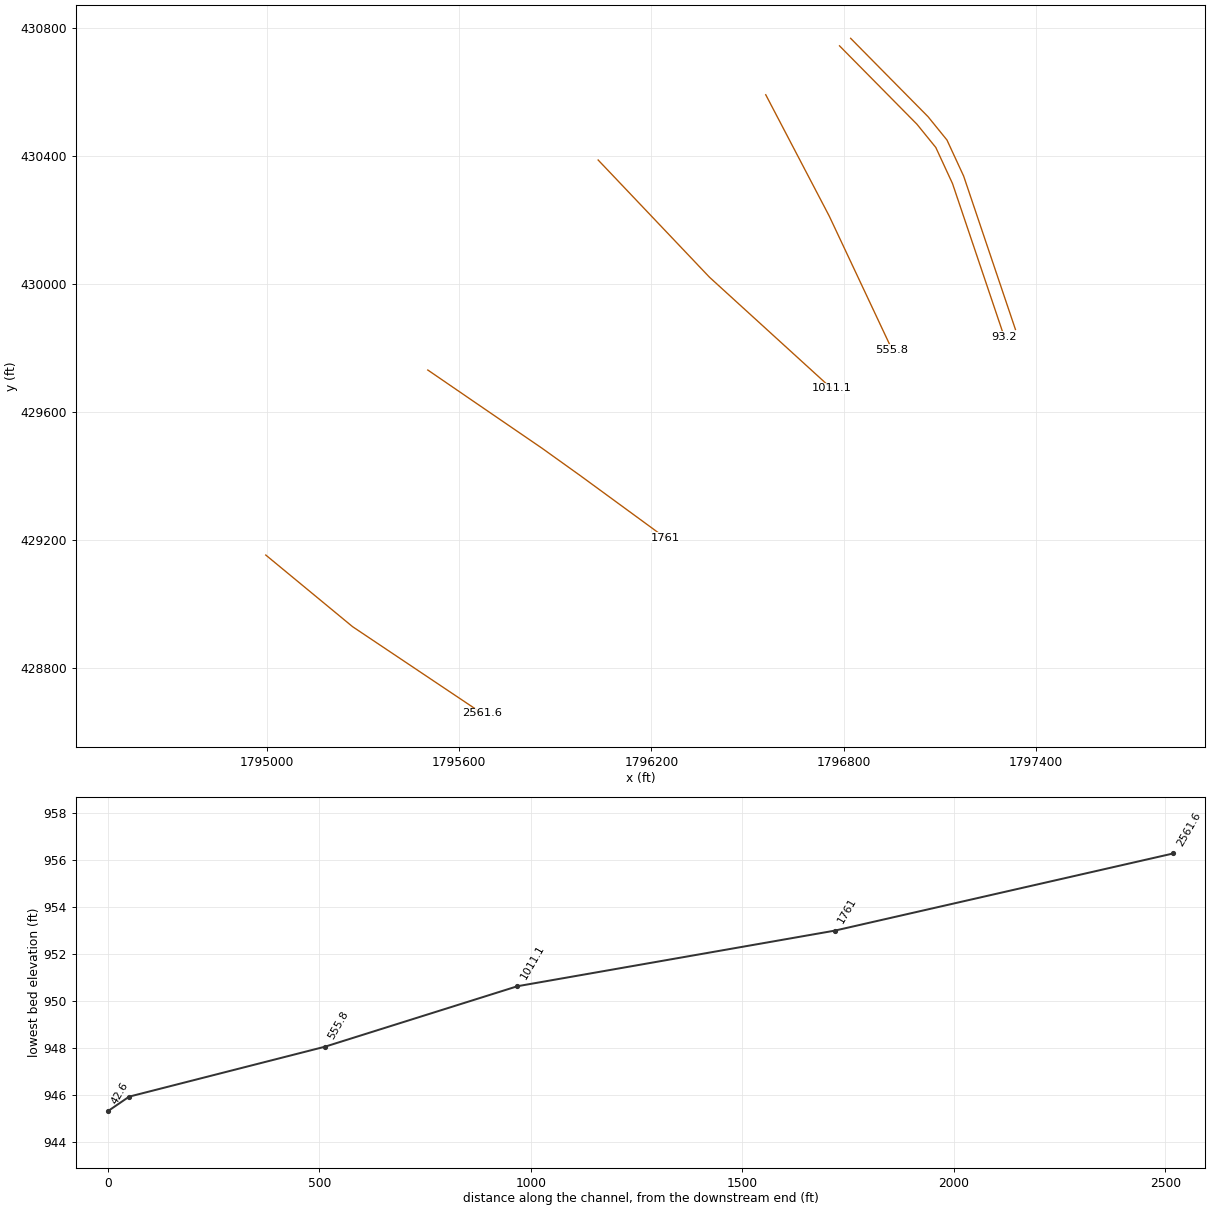
HEC-RAS study PedlarRun.prj: PedlarRun

--- PedlarRun.g01 (geometry) --- (continued)

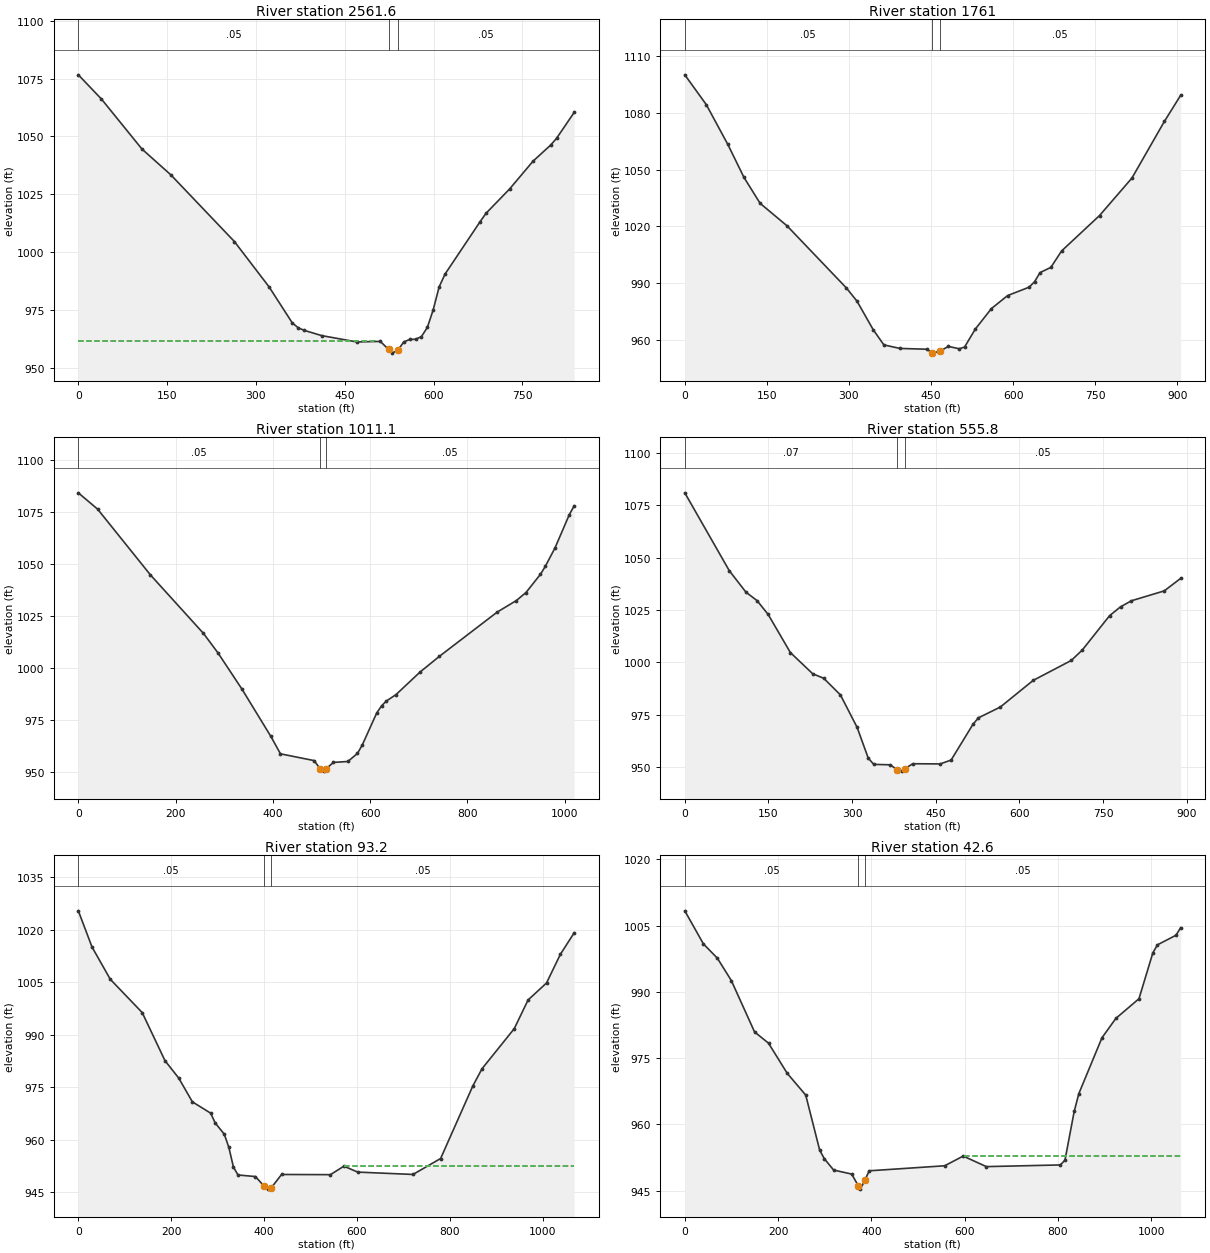
Type RM Length L Ch R = 1 ,2561.6  ,801.6,800.6,800.1
XS GIS Cut Line= 3
     1794997.421      429153.344     1795268.254      428929.386
       1795671.9      428658.553
#Sta/Elev= 30
       0 1076.62      39 1066.16   107.4 1044.55   156.2 1033.38   263.6 1004.53
   322.2  984.92   361.4  969.34   371.3  967.26   381.2  966.14     411  963.85
   470.5   961.1   510.2  961.34     524  957.87     530  956.27   539.9  957.63
   549.8  961.12   559.8  962.19   569.7  962.26   579.6  963.45   589.5  967.37
   599.4  974.99   609.4  984.88   619.3  990.42   678.8 1013.18   688.7 1016.76
   728.4 1027.24   768.1 1039.29   797.8 1046.24   807.8 1049.17   837.5 1060.36
#Mann= 3 , 0 , 0
       0     .05       0     524    .045       0   539.9     .05       0
#XS Ineff= 2 , 0
          500.41  961.38
Permanent Ineff=
       F       F
Bank Sta=524,539.9
XS Rating Curve= 0 ,0
Exp/Cntr=0.3,0.1

Type RM Length L Ch R = 1 ,1761    ,754.2,749.9,747
XS GIS Cut Line= 4
     1795502.629      429731.469       1795859.4      429486.678
     1795979.192       429400.74     1796242.213      429208.032
#Sta/Elev= 30
       0 1100.18    39.3 1084.41    78.7 1063.34   108.2  1045.9   137.7  1032.2
   186.8 1020.33     295  987.56   314.7  980.49   344.2  965.46   363.8  957.34
   393.3  955.47   442.5  955.06   450.9  953.29   452.3  952.99   465.9  953.98
   481.8  956.53   501.5  955.31   511.3  956.19     531  965.74   560.4  976.55
     590  983.43   629.5   987.9   639.4  990.82   649.3   995.6     669  998.34
   688.8 1007.07     758 1025.76   817.2 1045.58   876.5 1075.53   906.2 1089.33
#Mann= 3 , 0 , 0
       0     .05       0   450.9    .045       0   465.9     .05       0
Bank Sta=450.9,465.9
XS Rating Curve= 0 ,0
Exp/Cntr=0.3,0.1

Type RM Length L Ch R = 1 ,1011.1  ,460.8,455.2,448
XS GIS Cut Line= 3
     1796033.879      430387.719     1796381.102        430021.4
      1796761.31      429674.178
#Sta/Elev= 30
       0 1084.26    39.6 1076.44   148.4 1044.81   257.3 1016.77     287 1007.46
   336.5  989.99   395.9   967.3   415.7  958.93   484.9  955.69   497.5  951.68
   504.7  950.63   509.4  951.72   524.5  954.81   554.2  955.26     574  959.12
     584  963.23   613.6  978.57   623.6     982   633.5   984.3   653.3  987.39
   702.8  998.22   742.4 1005.74   861.2 1026.97   900.8 1032.55   920.6  1036.4
   950.3 1045.15   960.2 1048.92     980 1057.71  1009.7  1073.8  1019.6 1078.03
#Mann= 3 , 0 , 0
       0     .05       0   497.5    .045       0   509.4     .05       0
Bank Sta=497.5,509.4
XS Rating Curve= 0 ,0
Exp/Cntr=0.3,0.1

Type RM Length L Ch R = 1 ,555.8   ,462.7,462.7,458.2
XS GIS Cut Line= 3
     1796556.449      430591.712     1796754.853      430211.736
     1796950.546      429794.837
#Sta/Elev= 30
       0  1080.9    79.8 1043.73   109.7 1033.47   129.6 1029.45   149.5 1022.84
   189.4 1004.64   229.3  994.56   249.2  992.37   279.1  984.44     309  968.97
     329  954.27   338.9  951.28   368.8  951.08     380  948.78   388.8  948.06
     395  949.24   408.7  951.59     458   951.5   477.6  953.34   516.8  970.41
   526.6   973.5   565.8  978.65   624.6  991.34   693.2 1000.91   712.8 1005.85
   761.8 1022.27   781.4 1026.48     801 1029.38   859.8 1034.09   889.2 1040.05
#Mann= 3 , 0 , 0
       0     .07       0     380    .045       0     395     .05       0
Bank Sta=380,395
XS Rating Curve= 0 ,0
Exp/Cntr=0.3,0.1

Type RM Length L Ch R = 1 ,93.2    ,45.6,50.6,59.5
XS GIS Cut Line= 5
     1796786.484       430744.49     1797027.803      430499.698
     1797086.831      430426.782     1797138.914      430313.935
     1797300.372      429834.768
#Sta/Elev= 30
       0 1025.38    29.5 1015.04    68.8 1005.84   137.5  996.34   186.6   982.6
   216.1  977.65   245.5  970.86   284.8  967.63   294.6  964.85   314.3   961.6
   324.1  957.84   333.9  952.25   343.7  949.98   381.3  949.53     400  946.79
   409.4  945.94   415.5  946.36   437.6  950.12   542.7  950.07   571.8  952.49
   601.5   950.8   720.5  950.13     780  954.68   849.4  975.41   869.2  980.32
   938.6  991.76   968.3  999.94    1008 1004.78  1037.7 1012.94  1067.5  1019.1
#Mann= 3 , 0 , 0
       0     .05       0     400    .045       0   415.5     .05       0
#XS Ineff= 2 , 0
                           572.2          952.47
Permanent Ineff=
       F       F
Bank Sta=400,415.5
XS Rating Curve= 0 ,0
Exp/Cntr=0.3,0.1

Type RM Length L Ch R = 1 ,42.6    ,28.8,42.6,56.4
XS GIS Cut Line= 5
     1796821.206      430767.928     1797062.525      430523.136
     1797121.553      430450.219     1797173.636      430337.372
     1797335.095      429858.205
#Sta/Elev= 30
       0 1008.37    39.9 1000.88    69.8  997.64    99.7  992.58   149.5  980.94
   179.4  978.39   219.3  971.59   259.2  966.62   289.1  954.15     299  952.22
     319  949.64   357.7  948.73   371.9  946.07   376.4  945.32   385.8   947.3
   395.2  949.47     557  950.61   596.7  952.81   646.3  950.42   804.9   950.8
   814.8  951.88   834.6  962.93   844.6  966.98   894.1  979.61   923.9     984
   973.4  988.45  1003.2  998.86  1013.1 1000.67  1052.8 1002.84  1062.7 1004.55
#Mann= 3 , 0 , 0
       0     .05       0   371.9    .045       0   385.8     .05       0
#XS Ineff= 2 , 0
                          598.13          952.77
Permanent Ineff=
       F       F
Bank Sta=371.9,385.8
XS Rating Curve= 0 ,0
Exp/Cntr=0.3,0.1

Chan Stop Cuts=-1
Use User Specified Reach Order=0
Composite Channel Slope=5